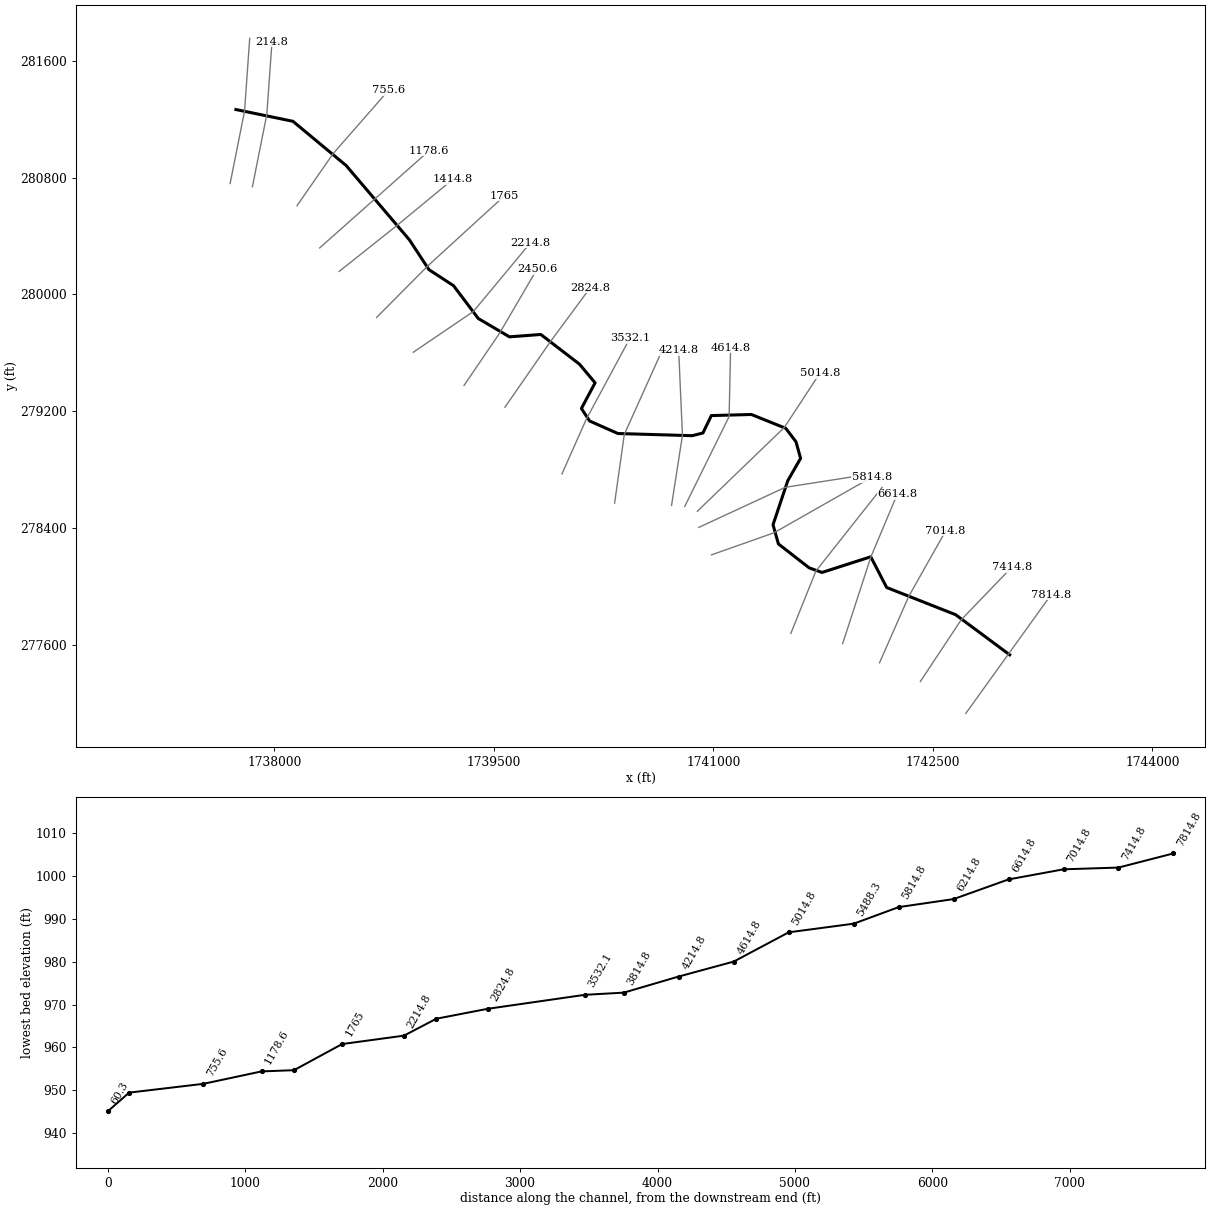
--- AnMorRn.prj (project) ---

Proj Title=AnMorRn
Current Plan=p01
Default Exp/Contr=0,0
English Units
Geom File=g01
Flow File=f01
Plan File=p01
BEGIN DESCRIPTION:
END DESCRIPTION:
DSS Export Rating Curves= 0
DSS Export Rating Curve Sorted= 0
DSS Export Volume Flow Curves= 0
DXF OffsetX= 0
DXF OffsetY= 0
DXF ScaleX= 0
DXF ScaleY= 0

--- AnMorRn.p01 (plan) ---

Plan Title=Floodplain
Program Version=4.00
Geom File=g01
Flow File=f01
K Sum by GR=0
Std Step Tol=0.01
Critical Tol=0.01
Num of Std Step Trials=20
Max Error Tol=0.3
Flow Tol Ratio=0.001
Split Flow NTrial=30
Split Flow Tol=0.02
Split Flow Ratio=0.02
Log Output Level=0
Friction Slope Method=1
Unsteady Friction Slope Method=2
Unsteady Bridges Friction Slope Method=1
Global Log Level=0
CheckData=False
Run HTab=0
Run UNet=0
Run PostProcess=0
UNET Theta=0
UNET Theta Warmup=0
UNET ZTol=0
UNET ZSATol=0
UNET MxIter=0
UNET MaxInSteps=0
UNET DtIC=0
UNET DtMin=0
UNET MaxCRTS=0
UNET WFStab=0
UNET SFStab=0
UNET WFX=0
UNET SFX=0
UNET DSS MLevel=0
UNET DZMax Abort=0
UNET Convert EG Bridges=0
UNET Use Existing IB Tables=0
UNET Froude Limit=0
UNET Froude Power=0
Write IC File=0
Echo Input=False
Echo Output=False
Write Detailed=0

--- AnMorRn.f01 (steady flow) ---

Flow Title=NFF Regression Equation
Program Version=4.00
Number of Profiles=1
Profile Names=P100yr
River Rch & RM=AnMorRn,Main      ,7814.8
1583.112
River Rch & RM=AnMorRn,Main      ,3532.1
1676.531
River Rch & RM=AnMorRn,Main      ,214.8
1853.475
River Rch & RM=AnMorRn,Main      ,60.3
1857.974
Boundary for River Rch & Prof#=AnMorRn,Main      ,1
Up Type=0
Dn Type=3
Dn Slope=0.007834

--- AnMorRn.g01 (geometry) ---

Geom Title=USGS 3m DEM
Program Version=4.00

River Reach=AnMorRn         ,Main
Reach XY= 30
     1743025.158      277532.221     1742655.819      277806.861
     1742184.297      277993.359     1742075.636      278203.589
     1741742.608      278096.372     1741654.838      278127.783
     1741444.624      278291.561     1741407.851      278423.111
     1741508.451      278724.236     1741596.142      278877.767
     1741564.741      278990.977     1741494.954      279083.258
     1741259.657       279177.99     1740986.194      279170.531
      1740928.88      279051.298     1740855.341      279032.846
     1740347.515      279047.736     1740154.498      279133.439
     1740098.466      279219.172     1740191.903      279394.798
     1740085.186      279522.564     1739821.048      279725.829
     1739606.429      279709.718     1739393.757      279835.248
     1739224.712      280059.938     1739056.679      280169.751
     1738923.322      280373.596     1738490.295      280883.263
     1738127.071      281185.656     1737737.663      281266.215

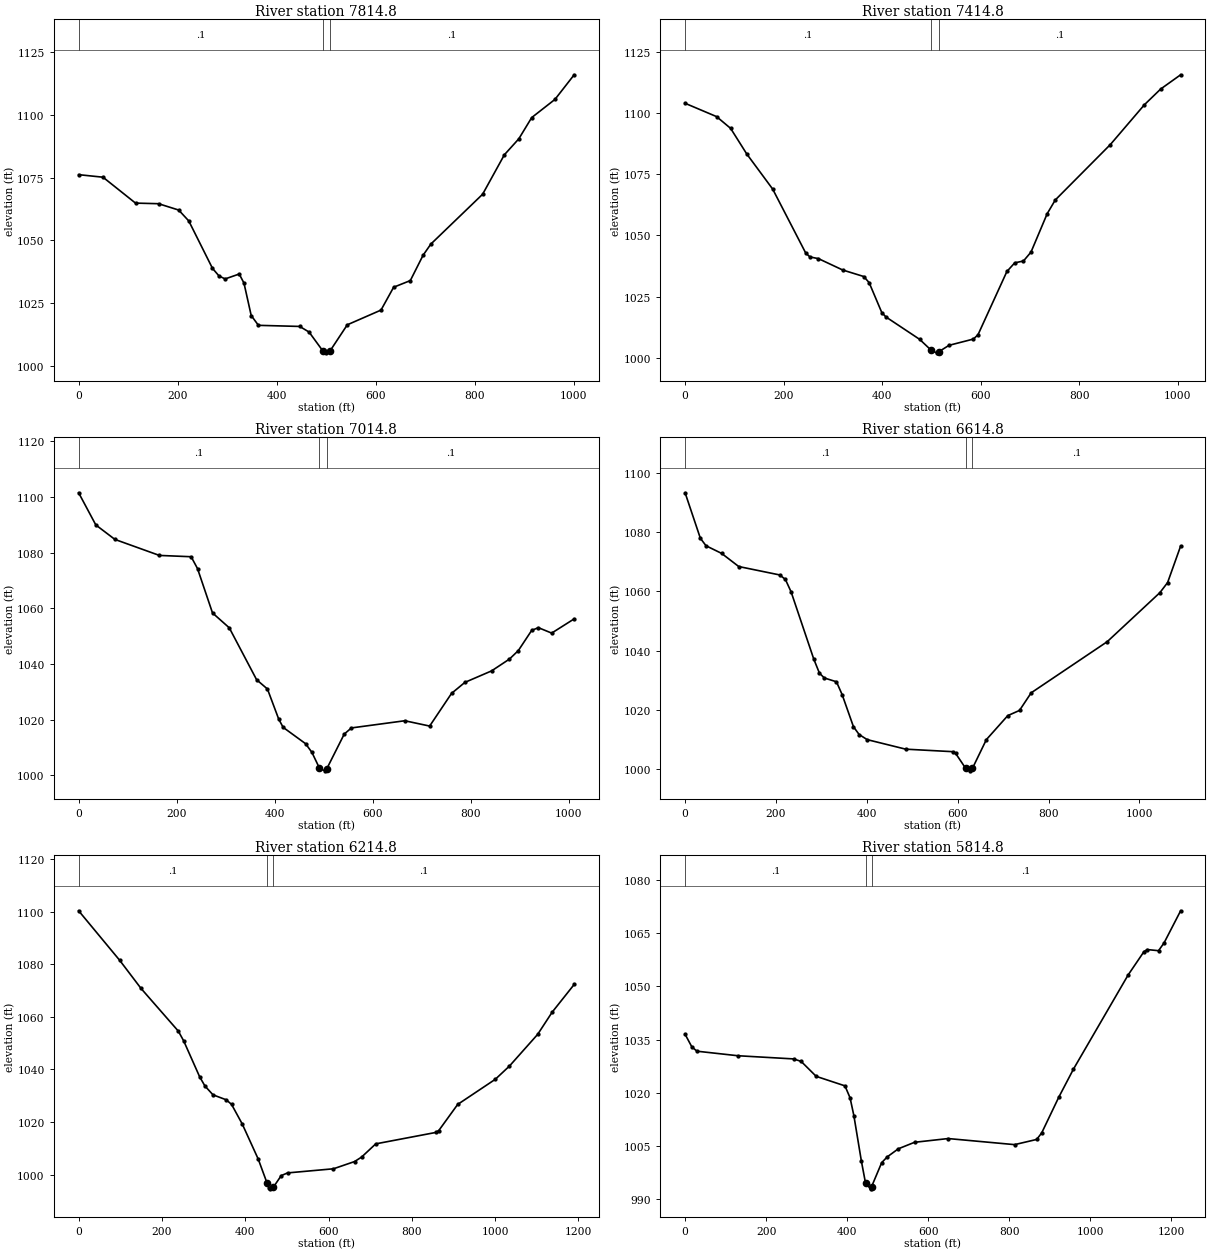
Type RM Length L Ch R = 1 ,7814.8  ,399.097,400,396.783
XS GIS Cut Line= 3
     1742725.374       277131.31     1743017.032      277538.048
     1743308.689      277944.787
#Sta/Elev= 30
       0 1076.13    49.2 1075.12   114.9 1064.83   161.4 1064.59   202.1 1062.07
   222.5 1057.74   270.4  1038.9   283.6 1035.87   295.9  1034.7   324.4 1036.65
     334 1033.04   348.6 1020.16   363.2 1016.26   446.6 1015.82   465.5 1013.59
     493 1006.18   500.1 1005.33     508 1006.12   542.7 1016.47   610.8 1022.32
   636.3  1031.4     670 1034.04   695.8 1044.11   711.5 1048.55   816.1 1068.36
     860 1084.03   889.2 1090.38   915.2 1098.81   962.2 1106.04    1001 1115.82
#Mann= 3 , 0 , 0
       0      .1       0     493    .045       0     508      .1       0
Bank Sta=493,508
XS Rating Curve= 0 ,0
Exp/Cntr=0.3,0.1

Type RM Length L Ch R = 1 ,7414.8  ,396.147,400,405.744
XS GIS Cut Line= 3
     1742414.514      277349.412     1742694.066       277772.64
     1743039.885      278132.892
#Sta/Elev= 30
       0 1103.97    63.9 1098.53    92.4 1093.73   125.1 1083.29   177.8 1068.92
     245 1042.75   253.6 1041.19   270.7 1040.51     320 1035.86   362.7  1033.2
   373.6 1030.71   399.3 1018.48   407.8 1016.67   476.1 1007.54   499.7 1003.06
   510.6 1002.02   514.7 1002.43   535.8 1005.09   585.3 1007.65   594.6  1009.4
   653.3 1035.26   669.2 1038.79   686.9 1039.54   702.2 1043.17   735.1 1058.87
   751.5 1064.47   863.3 1087.11   932.6 1103.41   965.5  1109.8    1006 1115.62
#Mann= 3 , 0 , 0
       0      .1       0   499.7    .045       0   514.7      .1       0
Bank Sta=499.7,514.7
XS Rating Curve= 0 ,0
Exp/Cntr=0.3,0.1

Type RM Length L Ch R = 1 ,7014.8  ,396.371,400,402.896
XS GIS Cut Line= 3
     1742135.345      277477.488     1742336.049      277934.015
     1742587.381      278380.708
#Sta/Elev= 30
       0 1101.48    35.1 1089.92      74 1084.73   164.8 1078.98   229.6 1078.51
   242.6 1074.25   273.2 1058.32   307.4 1052.98   363.2 1034.33   385.3    1031
   408.3 1020.18   417.3 1017.23   463.1 1011.36     476 1008.25   491.2 1002.66
   502.1 1001.61   506.2 1002.29     542 1014.81   556.6 1017.02   665.6  1019.6
   716.3 1017.69     761 1029.43   788.2 1033.38   842.7 1037.51   879.1 1041.75
   897.2 1044.79   924.5 1052.05   938.1 1053.04   965.3 1051.08  1011.2 1056.19
#Mann= 3 , 0 , 0
       0      .1       0   491.2    .045       0   506.2      .1       0
Bank Sta=491.2,506.2
XS Rating Curve= 0 ,0
Exp/Cntr=0.3,0.1

Type RM Length L Ch R = 1 ,6614.8  ,402.445,400,393.873
XS GIS Cut Line= 3
     1741883.354       277608.25     1742076.445       278202.63
     1742256.775      278632.176
#Sta/Elev= 30
       0 1093.42    33.6 1078.02    46.1 1075.47    80.4 1072.89   118.1 1068.44
   208.4 1065.59   220.8 1064.06   233.3 1059.88   283.3 1037.07   295.7 1032.34
   306.5  1030.7   333.2 1029.41   345.7 1025.06   370.6 1014.19   383.1 1011.55
   400.8 1009.82   485.6 1006.59   589.2 1005.74   595.4 1005.18   617.5 1000.12
   626.8  999.25   632.5 1000.09   663.1 1009.81   710.3 1017.95   736.1 1019.71
   761.8 1025.67   929.2 1042.99  1045.1 1059.59  1062.1 1063.01  1090.8 1075.38
#Mann= 3 , 0 , 0
       0      .1       0   617.5    .045       0   632.5      .1       0
Bank Sta=617.5,632.5
XS Rating Curve= 0 ,0
Exp/Cntr=0.3,0.1

Type RM Length L Ch R = 1 ,6214.8  ,419.189,400,391.51
XS GIS Cut Line= 3
     1741529.722      277679.265     1741700.937      278106.285
     1742153.111      278678.903
#Sta/Elev= 30
       0 1100.31    98.6 1081.48   149.8  1070.8   239.3 1054.59   252.1 1050.91
   290.5 1037.24   303.3 1033.71   322.6 1030.37   354.4 1028.48   367.2 1026.73
   392.8 1019.29   431.2 1005.95   452.6  996.74   456.8  994.94   459.6  994.65
   467.6   995.3   486.4  999.67   501.5  1000.7   611.8 1002.27   662.5 1005.02
   679.4 1006.73   713.3 1011.74   856.9 1016.06   864.6 1016.79     910 1026.72
  1000.4 1036.28  1034.4 1041.32    1102 1053.34  1136.9 1061.79  1189.7 1072.31
#Mann= 3 , 0 , 0
       0      .1       0   452.6    .045       0   467.6      .1       0
Bank Sta=452.6,467.6
XS Rating Curve= 0 ,0
Exp/Cntr=0.3,0.1

Type RM Length L Ch R = 1 ,5814.8  ,320.164,326.533,319.26
XS GIS Cut Line= 3
     1740987.022      278216.731     1741414.001      278367.629
     1742083.361      278749.165
#Sta/Elev= 30
       0 1036.47    16.8 1032.88    29.4 1031.69   130.2 1030.41   267.7 1029.51
   286.4 1028.81   323.6 1024.58   394.6 1021.89   407.2 1018.51   416.6 1013.48
   435.2 1000.58   445.4  994.37     458  992.77   460.4  993.41   485.3 1000.18
     499 1001.81   526.3 1004.09   566.3 1005.93   649.3 1006.99   813.3 1005.27
   867.9 1006.74   880.3  1008.6   922.6 1018.73   958.6 1026.62  1093.7 1053.27
  1132.7 1059.85  1141.3 1060.43  1168.6 1060.11  1182.3 1062.32  1223.2  1071.4
#Mann= 3 , 0 , 0
       0      .1       0   445.4    .045       0   460.4      .1       0
Bank Sta=445.4,460.4
XS Rating Curve= 0 ,0
Exp/Cntr=0.3,0.1

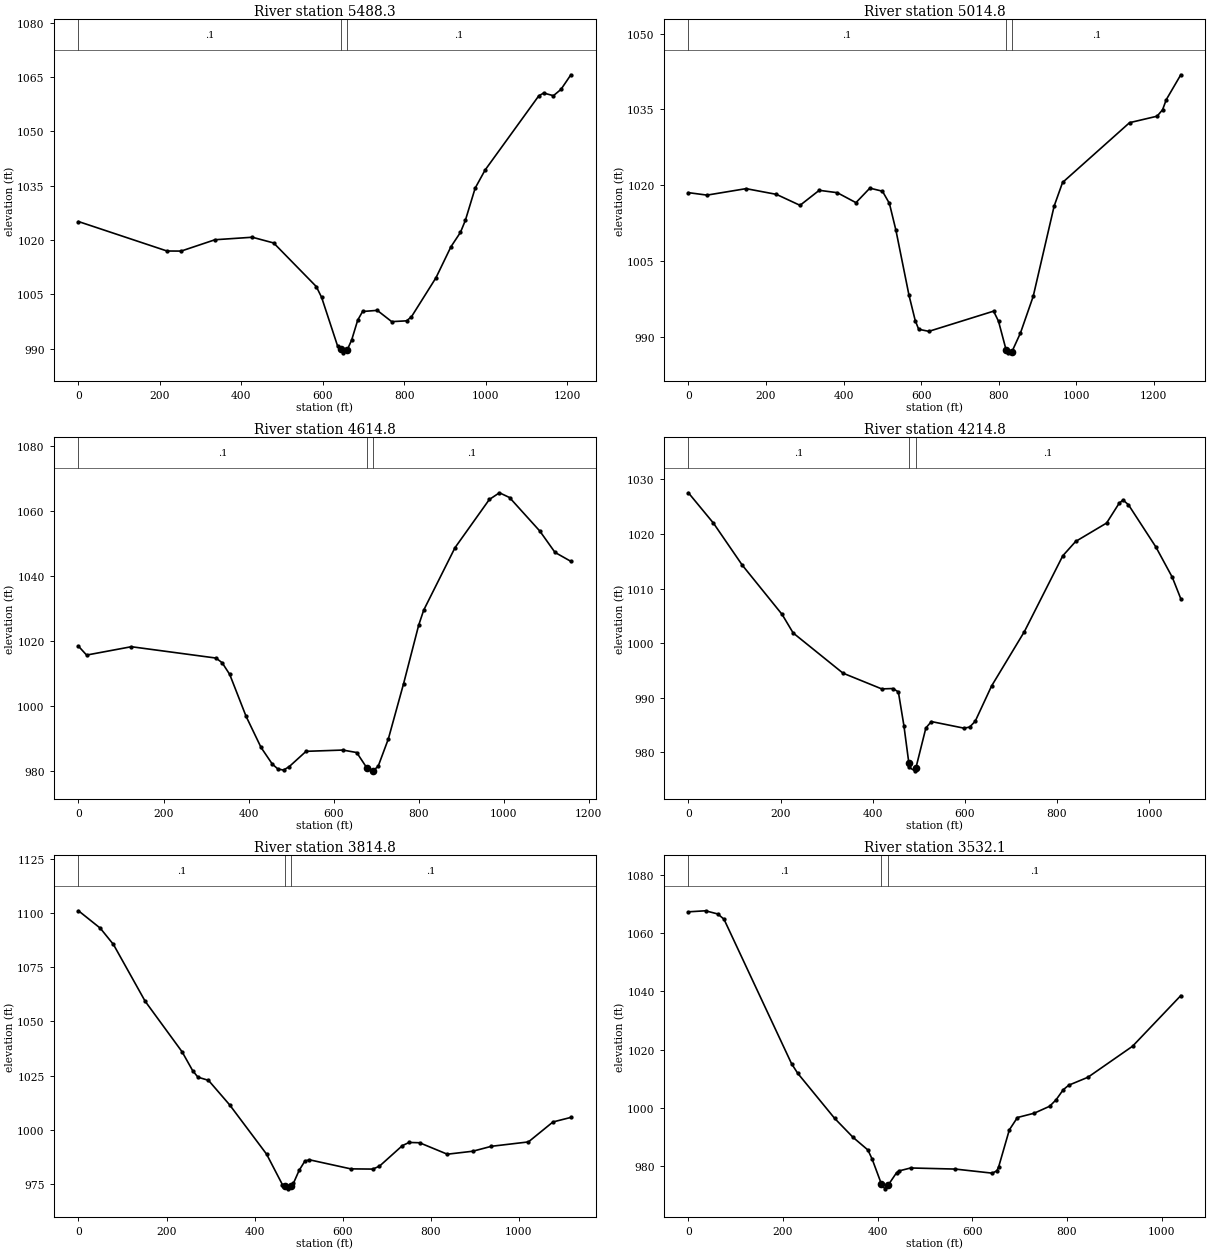
Type RM Length L Ch R = 1 ,5488.3  ,470.187,473.467,491.452
XS GIS Cut Line= 3
     1740900.663      278404.851     1741491.186      278679.209
     1742042.515      278765.436
#Sta/Elev= 30
       0 1025.13   217.4    1017   252.1 1016.98   335.3 1020.11   426.9  1020.8
   479.3 1019.22     584 1007.19   597.1  1004.2   636.4  990.75   644.7  990.06
   649.5   988.9   659.7  989.65   670.9  992.45   685.7  997.92   697.7 1000.31
   733.7 1000.62   769.2  997.51   805.8  997.73   817.8  998.87   877.9 1009.62
   914.7 1018.18     938 1022.14     950 1025.43   974.1 1034.34   998.5 1039.34
  1130.3 1059.81  1142.3 1060.59  1166.3 1059.86  1184.9  1061.6  1209.2 1065.63
#Mann= 3 , 0 , 0
       0      .1       0   644.7    .045       0   659.7      .1       0
Bank Sta=644.7,659.7
XS Rating Curve= 0 ,0
Exp/Cntr=0.3,0.1

Type RM Length L Ch R = 1 ,5014.8  ,392.606,400,412.457
XS GIS Cut Line= 3
     1740890.871      278515.491     1741485.244      279089.606
     1741727.654      279460.389
#Sta/Elev= 30
       0 1018.55      48 1018.06   148.7 1019.34   226.9 1018.21   287.8 1016.04
   337.3 1019.01   383.8 1018.54     432 1016.57   467.8 1019.44   500.3 1018.83
   518.2 1016.42     535 1011.12   568.7  998.27   584.9  993.23   593.7  991.54
   619.9  991.13   786.8  995.12   799.5  993.13   818.9  987.51     825  986.88
   833.9  987.08   856.1  990.81   888.9  998.04   942.9 1015.89   964.6 1020.56
  1137.3 1032.38  1208.2 1033.66  1222.4 1034.93    1232 1036.94  1269.4 1041.85
#Mann= 3 , 0 , 0
       0      .1       0   818.9    .045       0   833.9      .1       0
Bank Sta=818.9,833.9
XS Rating Curve= 0 ,0
Exp/Cntr=0.3,0.1

Type RM Length L Ch R = 1 ,4614.8  ,393.094,400,401.239
XS GIS Cut Line= 3
     1740804.895      278549.141     1741107.699      279163.833
     1741118.071      279636.616
#Sta/Elev= 30
       0 1018.37    19.1 1015.64   124.3 1018.21   323.5 1014.72     338 1013.27
   355.7 1009.69   394.3  996.77   429.4  987.23   455.9  982.11   469.1   980.6
   482.3  980.28   495.6  981.33   535.3  986.04   621.7  986.43   654.4  985.67
   677.7  981.05   692.7  980.07   693.2  980.04     705   981.5   728.8  989.86
   764.7 1006.88   800.1 1024.82   811.9 1029.45   885.5 1048.65   966.3 1063.49
   990.1 1065.55  1013.8 1064.09  1085.1 1053.77  1120.7 1047.22  1158.1 1044.46
#Mann= 3 , 0 , 0
       0      .1       0   677.7    .045       0   692.7      .1       0
Bank Sta=677.7,692.7
XS Rating Curve= 0 ,0
Exp/Cntr=0.3,0.1

Type RM Length L Ch R = 1 ,4214.8  ,399.696,400,389.266
XS GIS Cut Line= 3
     1740714.366       278555.27     1740788.839      279035.546
     1740763.099      279617.552
#Sta/Elev= 30
       0 1027.56    54.4 1021.99   116.8  1014.3   203.4 1005.24   227.4 1001.84
   335.5  994.47   419.6  991.58   443.7  991.65   455.7  991.03   467.7  984.85
   478.5  977.93   479.7  977.17   491.1  976.55   493.5     977   515.4  984.42
   527.3  985.59   598.6  984.37   610.5  984.59   622.4  985.64     658  992.12
   729.3 1002.11   812.5    1016   840.4 1018.63   907.6 1022.01   934.9 1025.65
   943.3 1026.23   955.1 1025.35  1014.5 1017.62  1050.2 1012.05  1068.6 1008.12
#Mann= 3 , 0 , 0
       0      .1       0   478.5    .045       0   493.5      .1       0
Bank Sta=478.5,493.5
XS Rating Curve= 0 ,0
Exp/Cntr=0.3,0.1

Type RM Length L Ch R = 1 ,3814.8  ,289.156,282.74,281.339
XS GIS Cut Line= 3
     1740325.216      278570.766     1740391.535      279041.535
     1740654.824       279627.76
#Sta/Elev= 30
       0 1101.01    49.4    1093    79.4 1085.47   151.3 1059.32   235.3 1035.96
   259.2  1027.3   271.2 1024.28   295.2 1022.81   343.2 1011.51   427.1  988.77
   463.1  974.69   467.9  974.02   475.1  972.78   482.9  974.32     488  975.31
     501   981.3   514.1   985.6   524.5  986.17   618.2  981.99   668.2  981.89
   683.3  983.22   735.3  992.69   750.5  994.17   774.4  994.04   837.4  988.75
   895.4  990.13   937.6   992.4  1021.6  994.42  1077.3 1003.62    1118 1005.72
#Mann= 3 , 0 , 0
       0      .1       0   467.9    .045       0   482.9      .1       0
Bank Sta=467.9,482.9
XS Rating Curve= 0 ,0
Exp/Cntr=0.3,0.1

Type RM Length L Ch R = 1 ,3532.1  ,711.162,707.315,704.307
XS GIS Cut Line= 3
     1739965.233      278770.661     1740132.461      279146.924
     1740430.335      279700.866
#Sta/Elev= 30
       0 1067.31    36.2 1067.67    62.2 1066.57    75.2 1064.79   218.1 1015.19
   231.1 1011.91     309  996.47     348  989.94   379.4   985.6   388.4  982.47
   407.8  973.99   415.3  972.27   422.8  973.69     440  977.81   444.7   978.4
   469.7  979.43   564.3  979.05   642.2  977.65     652  978.46   655.7  979.78
   678.3   992.5   695.4  996.74   730.9  998.22   763.5  1000.6     777  1002.8
   792.3 1006.27   803.9 1007.83   844.4 1010.55   938.7 1021.19  1040.7 1038.57
#Mann= 3 , 0 , 0
       0      .1       0   407.8    .045       0   422.8      .1       0
Bank Sta=407.8,422.8
XS Rating Curve= 0 ,0
Exp/Cntr=0.3,0.1

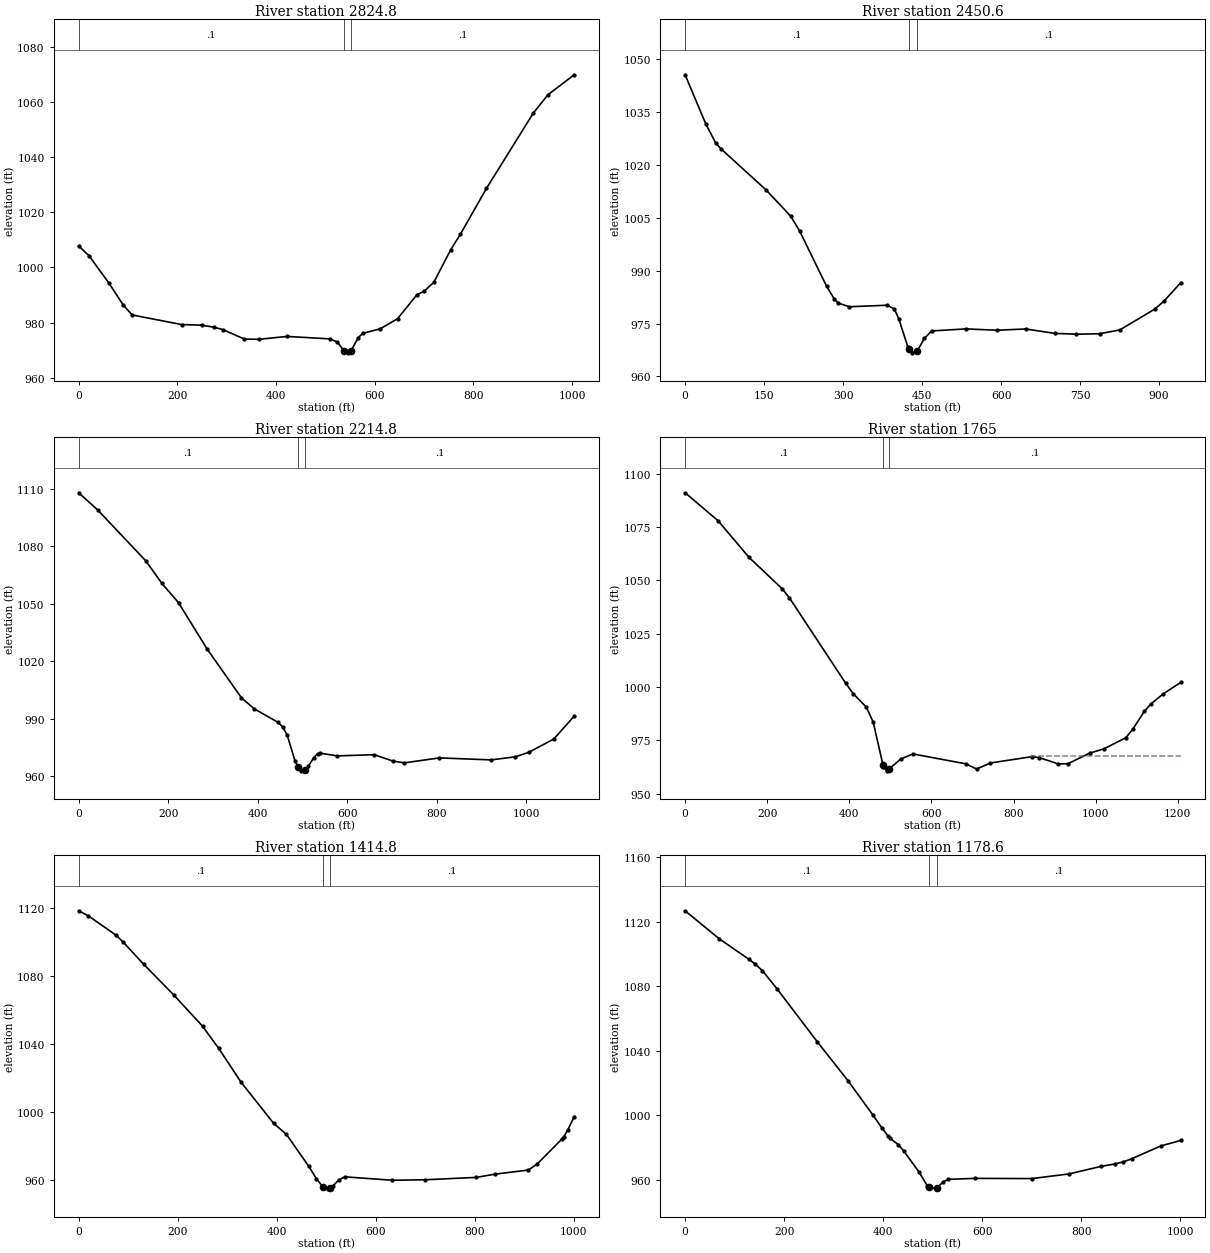
Type RM Length L Ch R = 1 ,2824.8  ,373.942,374.163,376.553
XS GIS Cut Line= 3
     1739575.906      279227.925     1739886.845      279677.349
      1740158.59      280045.773
#Sta/Elev= 30
       0 1007.85      21 1004.28    61.7  994.23    90.5  986.34   108.3  982.77
   208.7  979.27   249.3  979.05   275.3  978.28   292.7  977.41     336  974.01
   364.8  973.91   422.6  974.96   509.2  974.06   524.5  972.93   537.1  969.81
   546.5     969   552.1  969.82     567  974.55   575.5  976.04   611.7  977.76
   646.5  981.42   685.4  990.07   700.2  991.34   719.9  994.64   753.8 1006.35
   773.9 1012.14   826.5 1028.71   921.5 1056.08     951 1062.71  1004.3 1069.99
#Mann= 3 , 0 , 0
       0      .1       0   537.1    .045       0   552.1      .1       0
Bank Sta=537.1,552.1
XS Rating Curve= 0 ,0
Exp/Cntr=0.3,0.1

Type RM Length L Ch R = 1 ,2450.6  ,244.357,235.782,232.233
XS GIS Cut Line= 3
     1739296.322      279376.862     1739539.325      279734.834
     1739795.392      280173.807
#Sta/Elev= 30
       0 1045.65    39.1 1031.75    57.9 1026.35    67.8 1024.66   153.9 1012.93
   200.6 1005.48   217.7 1001.21   268.7  985.58   283.1  982.02   290.4  980.86
   311.6  979.77   383.5   980.2   397.2  979.15   405.7  976.37   422.8  968.42
   425.8  967.66   431.4  966.68   440.8  967.22   454.3  970.76   468.1   972.9
   533.3  973.48   591.8   973.1   646.7  973.46   701.7  972.21     743  971.97
   787.3  972.11   825.4  973.19   891.4  979.07   908.8  981.29   940.9  986.57
#Mann= 3 , 0 , 0
       0      .1       0   425.8    .045       0   440.8      .1       0
Bank Sta=425.8,440.8
XS Rating Curve= 0 ,0
Exp/Cntr=0.3,0.1

Type RM Length L Ch R = 1 ,2214.8  ,445.431,449.834,446.995
XS GIS Cut Line= 3
     1738949.509      279604.025     1739360.765      279883.753
     1739749.816      280353.303
#Sta/Elev= 30
       0 1107.92    42.4    1099   149.9 1072.41   185.9 1060.64   223.6  1050.4
   286.9  1026.4   363.6 1000.92   392.5  995.07   444.4  988.18   455.8  985.72
   466.1  981.34   483.2  968.08   489.9   964.9   497.9  962.83   503.2  962.72
   504.9  963.13   513.3  965.17   525.6  969.65     534  971.63   540.4  971.91
   577.6  970.53   660.5  971.14   702.6  967.79   727.9   966.9   806.2  969.47
   921.9  968.44   975.8  970.05  1005.6  972.38  1061.4  979.29  1107.2  991.27
#Mann= 3 , 0 , 0
       0      .1       0   489.9    .045       0   504.9      .1       0
Bank Sta=489.9,504.9
XS Rating Curve= 0 ,0
Exp/Cntr=0.3,0.1

Type RM Length L Ch R = 1 ,1765    ,352.888,350.166,348.564
XS GIS Cut Line= 3
     1738698.978      279842.712     1739049.726      280196.352
     1739572.262      280674.982
#Sta/Elev= 30
       0 1090.99    80.1 1077.94   155.7 1060.73   236.9 1045.95   253.8 1041.84
   390.7  1001.9   409.5  996.87   441.1  990.65   457.9  983.65   482.2  963.29
   483.1  962.59   491.5  960.76   497.2  961.72   525.1  966.27   554.6  968.68
   683.4  964.05   709.9  961.62   743.6  964.44   844.4   967.4     862  966.97
   908.8  964.01   932.3   964.1     985  969.04  1020.2  971.09  1072.9  976.24
  1090.5  980.34  1118.1  988.57  1134.2  992.06  1163.7  996.71  1206.7 1002.16
#Mann= 3 , 0 , 0
       0      .1       0   482.2    .045       0   497.2      .1       0
#XS Ineff= 2 , 0
                          843.22          967.82
Permanent Ineff=
       F       F
Bank Sta=482.2,497.2
XS Rating Curve= 0 ,0
Exp/Cntr=0.3,0.1

Type RM Length L Ch R = 1 ,1414.8  ,234.984,236.216,237.044
XS GIS Cut Line= 3
     1738442.586      280157.334     1738834.076      280469.133
     1739220.005      280787.969
#Sta/Elev= 30
       0 1118.26    18.9 1115.43      76 1103.81    89.9 1099.86   131.2 1086.85
     192 1068.77   250.4 1050.32     283 1037.28   328.6 1017.22     394  993.18
   419.6  986.74   465.2  967.81   480.3  960.66     493   955.9   495.5  954.99
   503.9  954.65     508  955.29     514   956.5   526.2  960.02   537.6  961.72
     634   959.7   700.4  959.99   803.5  961.39   841.2  963.29   908.6  965.72
   926.7  969.37   976.1  983.87   980.1  985.34   988.3  989.36  1001.1  997.14
#Mann= 3 , 0 , 0
       0      .1       0     493    .045       0     508      .1       0
Bank Sta=493,508
XS Rating Curve= 0 ,0
Exp/Cntr=0.3,0.1

Type RM Length L Ch R = 1 ,1178.6  ,418.716,422.965,425.788
XS GIS Cut Line= 3
     1738309.857      280318.444     1738683.718      280651.203
     1739057.579      280983.962
#Sta/Elev= 30
       0  1126.7    69.3 1109.26   128.2 1096.78   140.3 1093.97   156.2  1089.6
   186.1 1078.17   267.4 1045.36   328.9 1021.45   378.7 1000.42   397.3   992.2
   410.5  986.87   414.1  985.63   430.9  981.69   442.3  977.57   471.8  965.08
   489.6  956.15   493.3  955.72   505.9  954.36   508.3  954.86   521.8  958.72
   531.9  960.23   585.3  960.84     700  960.72   775.4  963.59   839.6  968.24
   868.2  969.76   885.1  971.06   901.9  972.96   960.7  980.92    1001  984.35
#Mann= 3 , 0 , 0
       0      .1       0   493.3    .045       0   508.3      .1       0
Bank Sta=493.3,508.3
XS Rating Curve= 0 ,0
Exp/Cntr=0.3,0.1

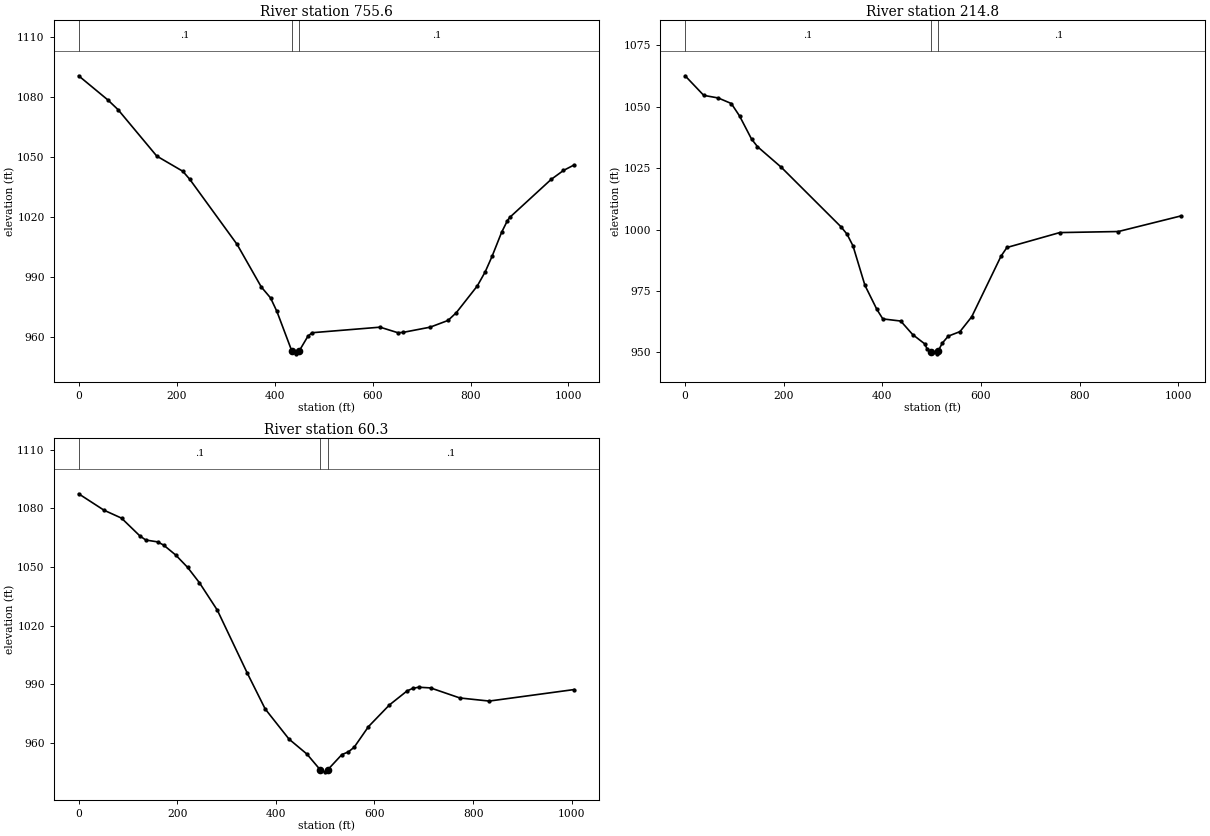
Type RM Length L Ch R = 1 ,755.6   ,530.465,540.82,555.435
XS GIS Cut Line= 3
     1738155.148      280607.794     1738400.764      280963.153
     1738782.252      281399.513
#Sta/Elev= 30
       0 1090.67    59.7 1078.57    80.5 1073.71   159.5 1050.47   212.5 1042.89
   226.7  1038.9   323.5 1006.24   372.9  984.93   391.8  979.46   404.8  972.66
   434.8  953.12   442.8  951.46   449.8  952.72   468.1  960.29   476.5  962.03
   615.4  964.81   651.5  962.05   661.6  962.17   717.7  964.82   754.1  968.18
     771  972.07   813.8  985.44   829.9  992.47   843.9 1000.22   863.5 1012.32
   875.4 1018.18   880.3 1019.82   964.5 1038.77   989.7 1043.26  1011.6 1046.04
#Mann= 3 , 0 , 0
       0      .1       0   434.8    .045       0   449.8      .1       0
Bank Sta=434.8,449.8
XS Rating Curve= 0 ,0
Exp/Cntr=0.3,0.1

Type RM Length L Ch R = 1 ,214.8   ,154.535,154.548,153.627
XS GIS Cut Line= 3
     1737850.243      280737.471     1737948.763      281233.082
     1737984.131       281731.48
#Sta/Elev= 30
       0 1062.59    37.8 1054.62    67.3 1053.55    93.7  1051.3   110.5 1046.21
   134.7 1036.85   146.8 1033.74   195.2 1025.32   316.3 1001.09   328.4  998.12
   340.5  993.36   364.7   977.3   388.9   967.5     401  963.62   437.3  962.75
   461.5  957.25   485.7   953.5   491.4  951.18   497.8  949.98   509.9   949.4
   512.8  950.45   521.8   953.8   533.7   956.6   557.5  958.45   581.3  964.49
   640.8  989.19   652.7  992.69   759.8  998.76   878.7  999.19    1005 1005.51
#Mann= 3 , 0 , 0
       0      .1       0   497.8    .045       0   512.8      .1       0
Bank Sta=497.8,512.8
XS Rating Curve= 0 ,0
Exp/Cntr=0.3,0.1

Type RM Length L Ch R = 1 ,60.3    ,63.214,60.266,55.417
XS GIS Cut Line= 3
     1737697.961      280759.756     1737796.482      281255.367
      1737831.85      281753.765
#Sta/Elev= 30
       0 1087.54    51.4 1079.13      87 1075.06   124.1 1065.97   136.2 1063.84
   160.4 1062.88   172.5 1061.22   196.7  1056.2   220.9 1049.86   245.1 1041.92
   281.4 1027.85     342  995.66   378.3  977.29   426.7  961.82     463  954.16
   490.4  945.96   499.3  945.05   505.4  946.16   533.9   953.9     547  955.26
   558.9  957.68   587.8  968.22   630.3  979.33   666.1  986.51   677.5  987.82
   689.5  988.41   713.7  988.06   773.2   982.9   832.7  981.32    1005  987.22
#Mann= 3 , 0 , 0
       0      .1       0   490.4    .045       0   505.4      .1       0
Bank Sta=490.4,505.4
XS Rating Curve= 0 ,0
Exp/Cntr=0.3,0.1

Chan Stop Cuts=-1
Use User Specified Reach Order=0